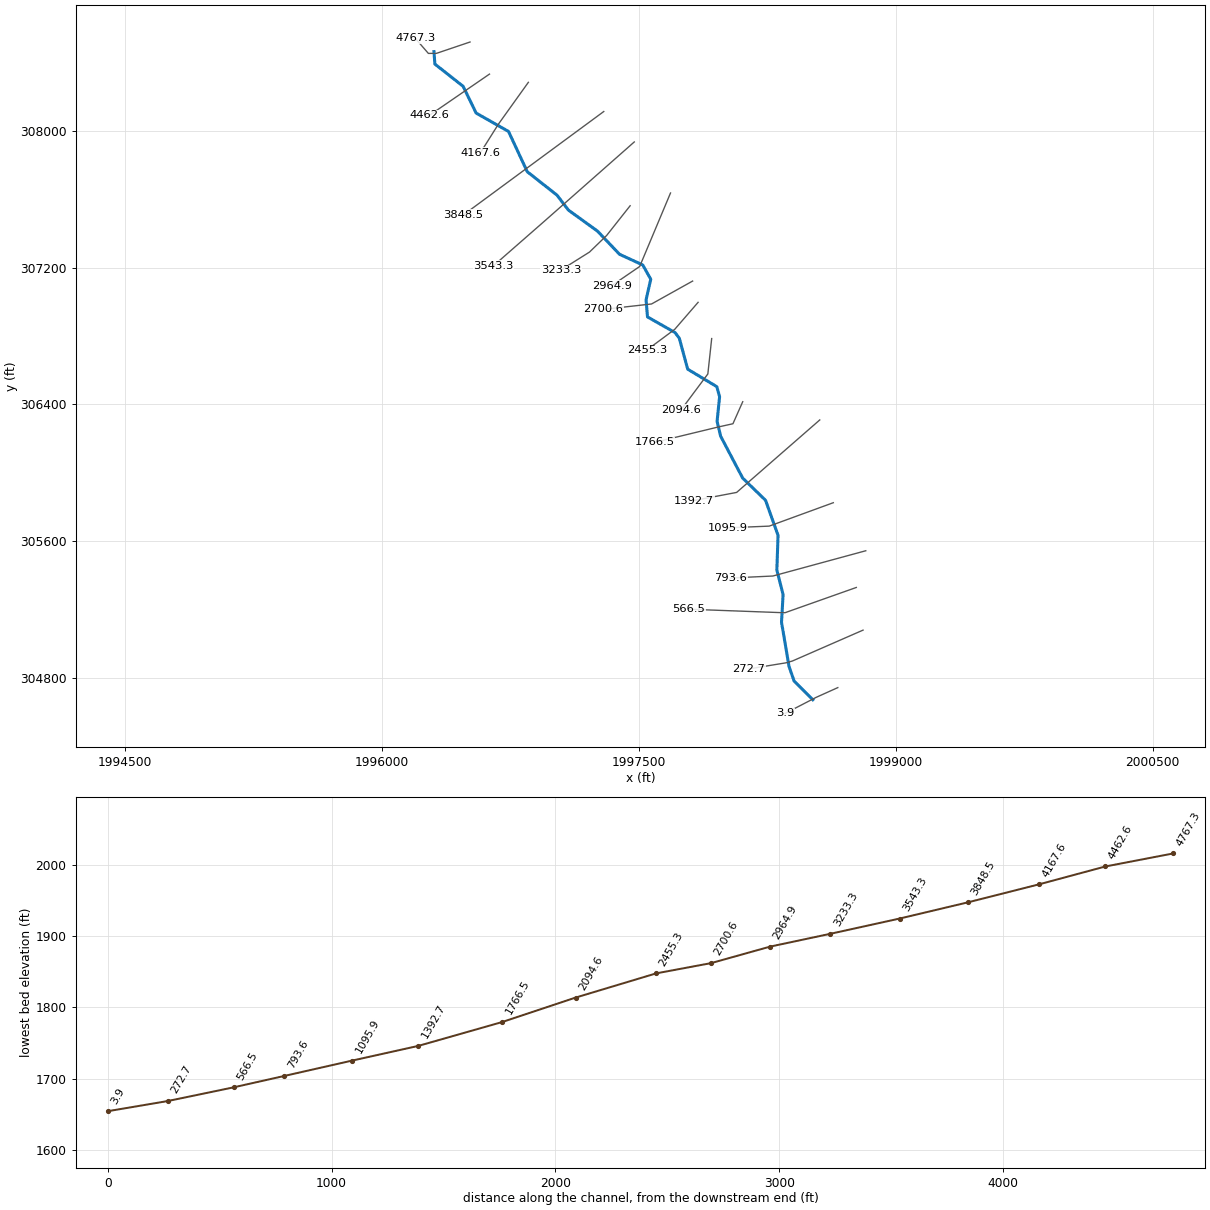
--- LHFMdwCrk.prj (project) ---

Proj Title=LHFMdwCrk
Current Plan=p01
Default Exp/Contr=0,0
English Units
Geom File=g01
Flow File=f01
Plan File=p01
BEGIN DESCRIPTION:
END DESCRIPTION:
DSS Export Rating Curves= 0
DSS Export Rating Curve Sorted= 0
DSS Export Volume Flow Curves= 0
DXF OffsetX= 0
DXF OffsetY= 0
DXF ScaleX= 0
DXF ScaleY= 0

--- LHFMdwCrk.p01 (plan) ---

Plan Title=Floodplain
Program Version=4.00
Geom File=g01
Flow File=f01
K Sum by GR=0
Std Step Tol=0.01
Critical Tol=0.01
Num of Std Step Trials=20
Max Error Tol=0.3
Flow Tol Ratio=0.001
Split Flow NTrial=30
Split Flow Tol=0.02
Split Flow Ratio=0.02
Log Output Level=0
Friction Slope Method=1
Unsteady Friction Slope Method=2
Unsteady Bridges Friction Slope Method=1
Global Log Level=0
CheckData=False
Run HTab=0
Run UNet=0
Run PostProcess=0
UNET Theta=0
UNET Theta Warmup=0
UNET ZTol=0
UNET ZSATol=0
UNET MxIter=0
UNET MaxInSteps=0
UNET DtIC=0
UNET DtMin=0
UNET MaxCRTS=0
UNET WFStab=0
UNET SFStab=0
UNET WFX=0
UNET SFX=0
UNET DSS MLevel=0
UNET DZMax Abort=0
UNET Convert EG Bridges=0
UNET Use Existing IB Tables=0
UNET Froude Limit=0
UNET Froude Power=0
Write IC File=0
Echo Input=False
Echo Output=False
Write Detailed=0

--- LHFMdwCrk.f01 (steady flow) ---

Flow Title=NFF Regression Equation
Program Version=4.00
Number of Profiles=1
Profile Names=P100yr
River Rch & RM=LHFMdwCrk,Main      ,4767.3
737.1319
River Rch & RM=LHFMdwCrk,Main      ,2094.6
1057.884
River Rch & RM=LHFMdwCrk,Main      ,2094.6
780.6943
River Rch & RM=LHFMdwCrk,Main      ,272.7
1080.360
Boundary for River Rch & Prof#=LHFMdwCrk,Main      ,1
Up Type=0
Dn Type=3
Dn Slope=0.059633

--- LHFMdwCrk.g01 (geometry) ---

Geom Title=USGS 3m DEM
Program Version=4.10

River Reach=LHFMdwCrk       ,Main
Reach XY= 30
      1996304.32      308464.029     1996309.529      308391.112
     1996474.459      308260.904     1996550.522      308104.293
     1996739.533      307996.973     1996848.954      307761.308
      1997023.07      307623.751     1997089.042      307536.946
     1997259.181      307413.682     1997387.653      307278.265
      1997523.07      307215.765     1997569.945      307132.432
     1997542.624      307012.275     1997550.848      306911.946
     1997712.306      306819.932     1997736.612      306786.946
     1997785.666      306605.995     1997955.362       306503.96
     1997971.813      306445.499     1997957.098      306300.835
     1997977.931      306214.029     1998106.404      305969.238
     1998240.084      305839.029     1998313.001      305634.168
     1998306.056      305431.043     1998342.515      305286.946
     1998333.247      305125.998     1998377.237      304866.807
     1998406.751      304781.737     1998516.126      304672.363

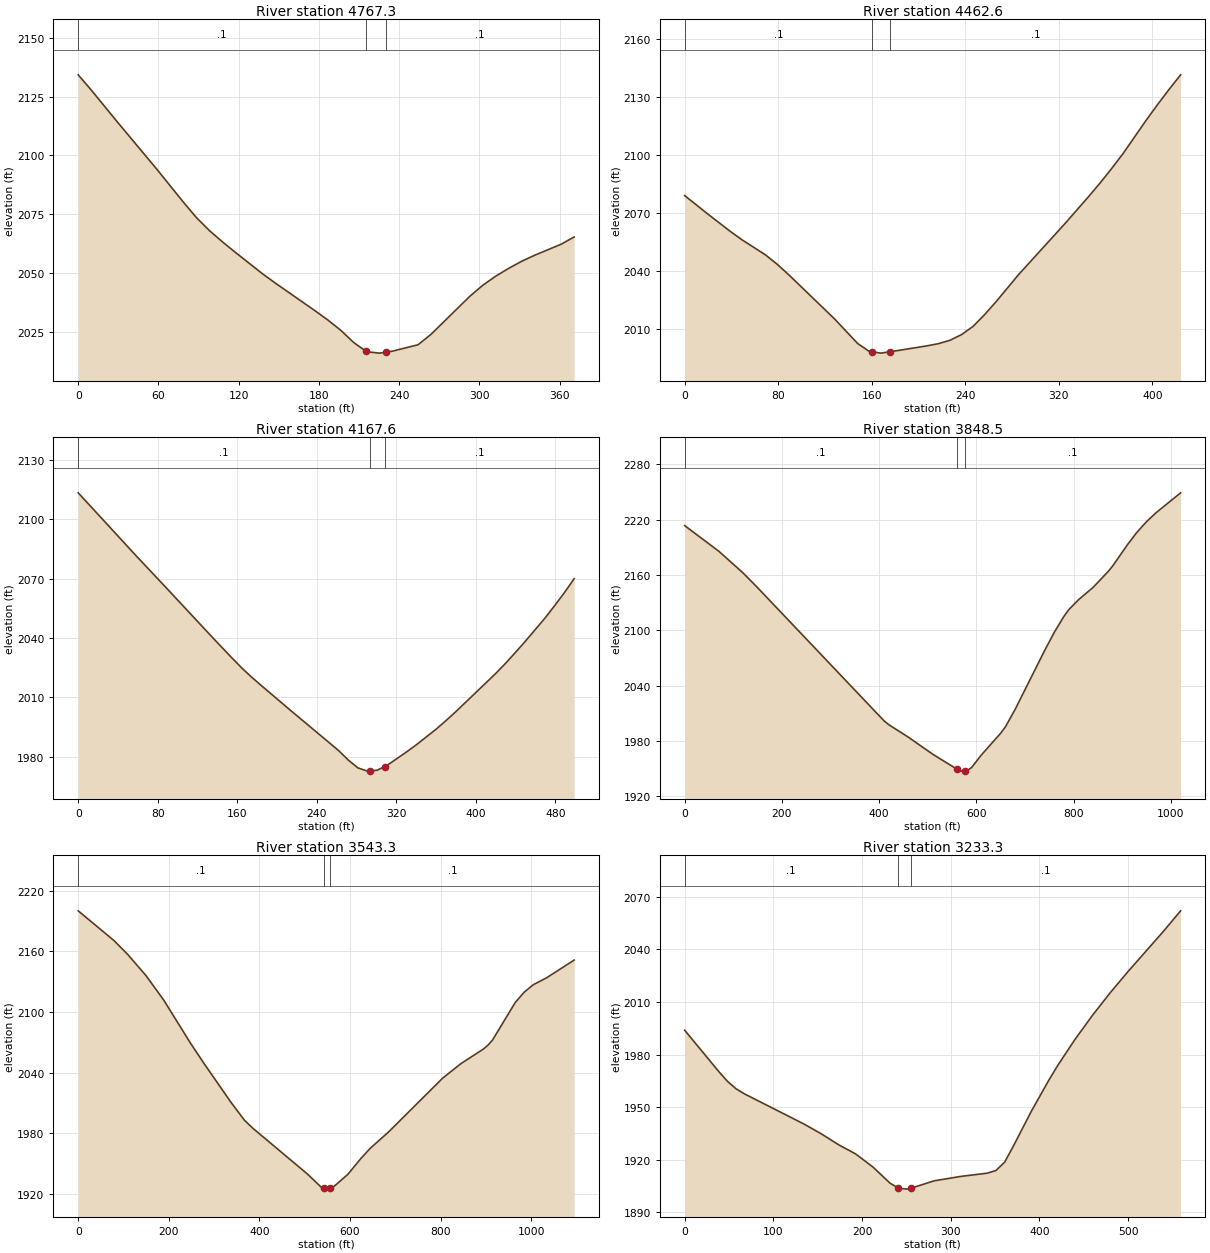
Type RM Length L Ch R = 1 ,4767.3  ,293.5,304.4,316.9
XS GIS Cut Line= 4
     1996514.988      308520.144     1996319.653      308453.985
     1996271.688      308453.319      1996195.41      308541.588
#Sta/Elev= 30
       0 2134.22     9.8 2127.73    29.5 2114.06    58.9 2094.07    78.6 2080.19
    88.4 2073.59    98.2 2068.04     108 2063.24   117.8 2058.71   137.5 2049.88
   147.3 2045.83   176.8 2034.16   186.6 2030.15   196.4 2025.73   206.2 2020.46
   215.2 2016.86   215.8 2016.62   225.4 2016.04   230.22016.457     235 2016.87
   254.2  2019.6   263.9 2024.05   293.1 2040.29   302.8 2044.96   312.5 2048.81
   322.3 2052.16     332 2055.14   341.7 2057.68   361.1 2062.27   370.9 2065.36
#Mann= 3 , 0 , 0
       0      .1       0   215.2    .045       0   230.2      .1       0
Bank Sta=215.2,230.2
XS Rating Curve= 0 ,0
Exp/Cntr=0.3,0.1

Type RM Length L Ch R = 1 ,4462.6  ,287.7,295,303.5
XS GIS Cut Line= 2
     1996628.426      308332.407     1996279.053      308091.991
#Sta/Elev= 30
       0  2079.1    19.7 2069.61    39.4 2060.42    49.3 2056.14      69  2048.5
    78.9 2043.72    88.8  2038.3   128.2 2015.34   147.9 2002.68   157.8 1998.58
   160.51998.336   167.7 1997.68   175.51998.363   207.1 2001.43     217 2002.57
   226.8  2004.3   236.7 2007.22   246.6 2011.49   256.4 2017.52   266.3 2024.27
     286 2038.58   325.5 2064.82   345.2 2078.44   355.1 2085.51   364.9 2092.91
   374.8 2100.75   394.5 2117.91   404.4 2126.14   414.2 2133.96   424.1 2141.51
#Mann= 3 , 0 , 0
       0      .1       0   160.5    .045       0   175.5      .1       0
Bank Sta=160.5,175.5
XS Rating Curve= 0 ,0
Exp/Cntr=0.3,0.1

Type RM Length L Ch R = 1 ,4167.6  ,325.3,318.5,310.5
XS GIS Cut Line= 3
     1996855.335      308284.194     1996680.491      308039.552
     1996575.132      307871.708
#Sta/Elev= 30
       0 2113.44    58.2 2081.65    87.3  2066.1   135.8 2039.93   155.2 2029.68
   164.9 2024.72   174.6 2020.18   184.3 2015.96   213.4 2003.53   261.9 1983.16
   271.6 1978.38   281.3 1974.38     291 1972.73   293.21972.837   300.7 1973.19
   308.21975.005   310.6 1975.59   330.4 1982.47   340.3  1986.1   360.2    1994
   370.1 1998.33     380 2002.86   419.6  2021.9   429.5 2027.03   439.4 2032.49
   449.3  2038.1   469.2 2049.89     479 2056.21     489 2062.91   498.9 2070.01
#Mann= 3 , 0 , 0
       0      .1       0   293.2    .045       0   308.2      .1       0
Bank Sta=293.2,308.2
XS Rating Curve= 0 ,0
Exp/Cntr=0.3,0.1

Type RM Length L Ch R = 1 ,3848.5  ,303.2,305.1,306.9
XS GIS Cut Line= 2
     1997295.621      308113.492      1996474.86      307507.727
#Sta/Elev= 30
       0 2213.67      70 2185.97     120 2162.38     150 2146.34     410 2002.01
     420 1997.74     460 1984.27     510 1965.84     561 1949.22     570 1947.42
     576 1947.53   580.1 1947.61   590.1 1951.29   610.1 1964.83   650.1 1988.62
   660.1 1995.76   680.1 2014.76   740.1 2077.89   760.1  2097.8   780.1 2115.25
   790.1 2122.51   810.1 2133.29   840.1 2146.69   870.1 2163.34   880.1  2169.7
   910.1 2192.45   930.1 2206.33   950.1 2217.99   970.1 2227.86  1020.1 2249.21
#Mann= 3 , 0 , 0
       0      .1       0     561    .045       0     576      .1       0
Bank Sta=561,576
XS Rating Curve= 0 ,0
Exp/Cntr=0.3,0.1

Type RM Length L Ch R = 1 ,3543.3  ,309,310,311
XS GIS Cut Line= 3
     1997473.701      307935.455     1996945.861      307469.053
     1996652.235      307211.659
#Sta/Elev= 30
       0 2200.19    79.4 2170.59   109.1  2157.1   148.8 2136.55   188.5    2112
     248  2069.1   277.8 2049.04   337.3 2010.59   367.1 1992.84   386.9 1984.42
     506 1939.65   535.7 1926.92   541.81925.539   545.6 1924.68   556.81925.385
   565.5 1927.67   595.2 1939.31     625 1955.53   644.8 1965.15   684.5 1981.01
   804.5 2034.51   844.6 2048.85   894.6 2063.37   904.6  2067.2   914.6 2072.28
   964.7 2109.39   984.7 2119.76  1004.7 2127.06  1034.8  2134.1  1094.8 2151.46
#Mann= 3 , 0 , 0
       0      .1       0   541.8    .045       0   556.8      .1       0
Bank Sta=541.8,556.8
XS Rating Curve= 0 ,0
Exp/Cntr=0.3,0.1

Type RM Length L Ch R = 1 ,3233.3  ,260,268.5,274.8
XS GIS Cut Line= 4
     1997449.554      307562.206     1997312.173      307388.111
      1997212.38      307291.293     1997044.517      307185.593
#Sta/Elev= 30
       0  1993.9    38.6 1970.23    48.2 1964.78    57.8 1960.53    67.5 1957.57
     135 1940.26   154.3 1934.72   173.6 1928.57   192.8 1923.31   212.1 1915.94
   231.7  1906.6   240.21904.119   241.6 1903.71   251.6 1903.26   255.21903.791
   281.4 1908.01   311.2  1910.5     341 1912.35   350.9 1913.85   360.8 1918.62
   370.7 1927.87   390.6  1947.4   410.4 1965.22   420.3 1973.52   440.2 1988.72
     460  2002.5   479.8 2015.26   499.7 2027.24   539.3 2049.97   559.2 2061.98
#Mann= 3 , 0 , 0
       0      .1       0   240.2    .045       0   255.2      .1       0
Bank Sta=240.2,255.2
XS Rating Curve= 0 ,0
Exp/Cntr=0.3,0.1

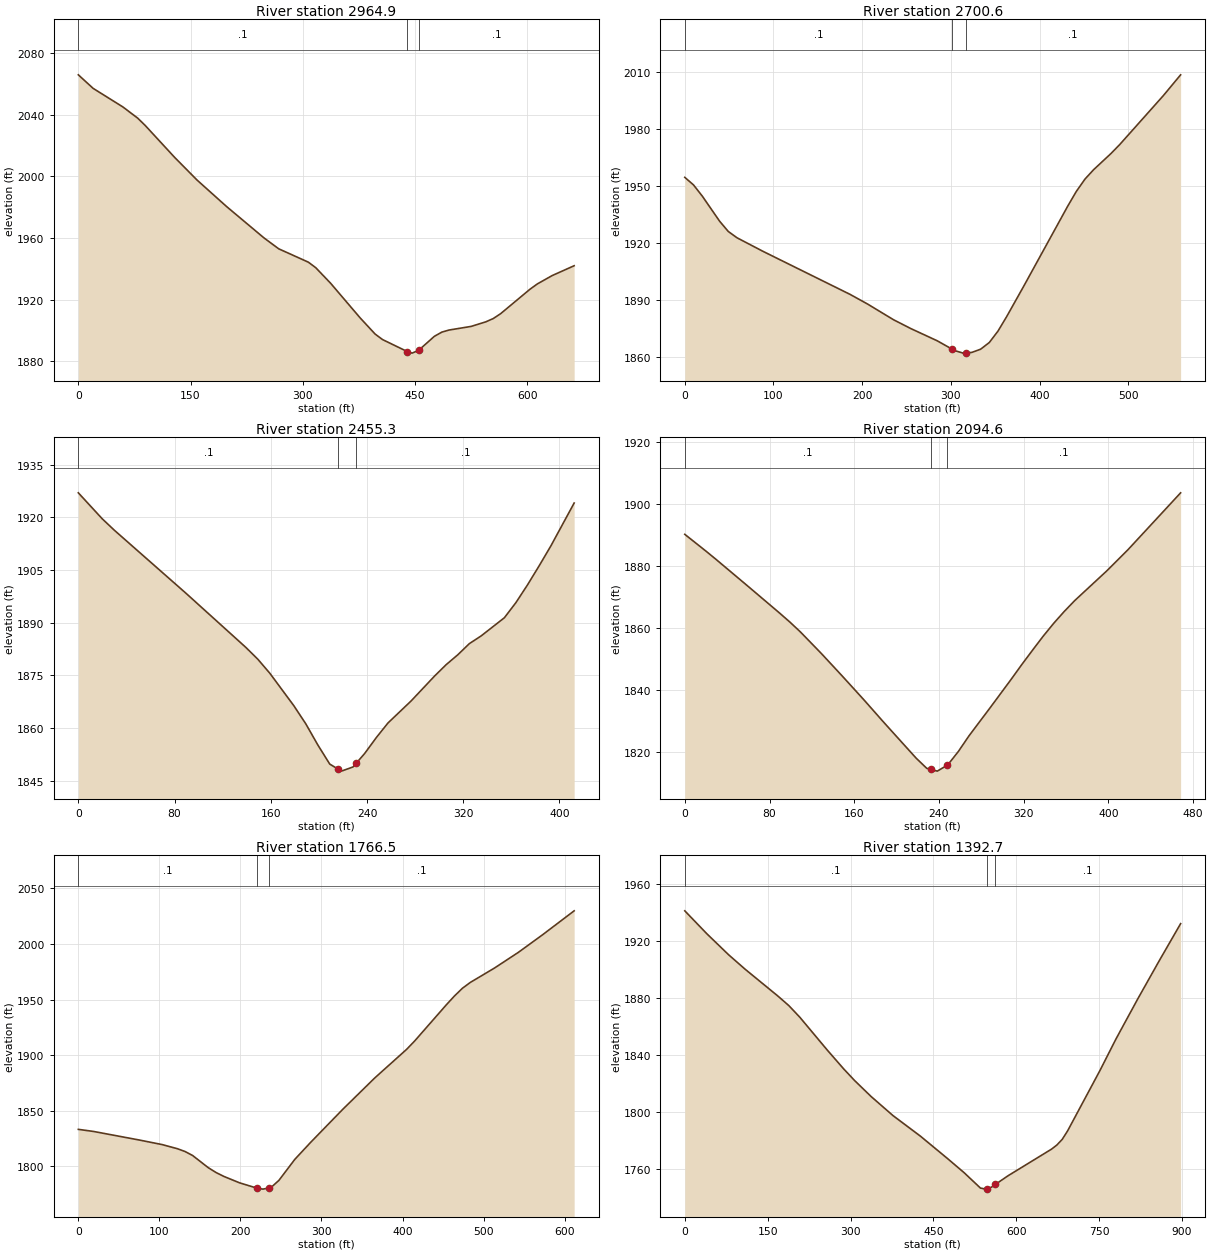
Type RM Length L Ch R = 1 ,2964.9  ,286.4,263.8,243.5
XS GIS Cut Line= 3
     1997685.233      307636.818     1997505.217      307206.911
     1997342.965      307095.585
#Sta/Elev= 30
       0 2065.85    19.8 2057.06    59.5 2045.04    79.3 2037.78    89.2 2033.11
   128.9 2012.22   158.7 1997.59   198.3 1980.36   247.9 1960.18   267.8 1953.01
   307.4 1944.35   317.3 1940.78   337.2 1930.68   376.8 1908.14   396.7 1897.72
   406.6 1894.14   439.91886.302   446.2 1885.33   454.91887.146   475.9 1896.21
   485.8 1898.93   495.6 1900.31   525.1 1902.66   544.8 1905.64   554.6 1907.74
   564.5 1910.91   603.8 1926.79   613.6 1930.22   633.3 1935.61   662.8 1942.02
#Mann= 3 , 0 , 0
       0      .1       0   439.9    .045       0   454.9      .1       0
Bank Sta=439.9,454.9
XS Rating Curve= 0 ,0
Exp/Cntr=0.3,0.1

Type RM Length L Ch R = 1 ,2700.6  ,232.6,245.3,256.3
XS GIS Cut Line= 3
     1997814.324       307121.64     1997574.564      306987.608
     1997292.039      306955.835
#Sta/Elev= 30
       0 1954.62     9.8 1950.65    19.6 1944.84    39.2 1931.59      49 1926.17
    58.9 1922.83    88.3 1915.68   186.4 1893.06     206 1888.01   235.4 1879.72
   255.1 1875.03   284.5 1868.69   301.51864.235   304.1 1863.53   313.9 1862.18
   316.5 1862.28   323.7 1862.57   333.5 1864.24   343.3 1867.76   353.1 1873.76
   362.9  1881.4   382.5  1897.7   431.5 1939.29   441.3 1947.14   451.2 1953.73
     461 1958.69   480.6  1967.2   490.4  1971.9   539.4 1997.54     559 2008.54
#Mann= 3 , 0 , 0
       0      .1       0   301.5    .045       0   316.5      .1       0
Bank Sta=301.5,316.5
XS Rating Curve= 0 ,0
Exp/Cntr=0.3,0.1

Type RM Length L Ch R = 1 ,2455.3  ,355.6,360.4,366.9
XS GIS Cut Line= 3
       1997846.3      306997.286      1997709.73       306839.09
     1997546.668      306717.787
#Sta/Elev= 30
       0 1926.97    19.9 1919.57    29.9 1916.34    89.6 1898.36   139.3 1882.98
   149.3  1879.6   159.2 1875.64   179.1 1866.43   189.1 1861.25     199  1855.3
     209  1849.8   216.2 1848.31   218.7 1847.79   228.4 1848.98   231.21850.095
     238 1852.79   247.7 1857.32   257.4 1861.48   276.7 1867.77   296.1 1874.82
   305.8 1878.08   315.4 1880.87   325.1 1884.07   334.8 1886.24   354.2 1891.43
   363.8 1895.74   373.5 1900.82   383.2 1906.26   392.9  1911.9   412.2 1924.07
#Mann= 3 , 0 , 0
       0      .1       0   216.2    .045       0   231.2      .1       0
Bank Sta=216.2,231.2
XS Rating Curve= 0 ,0
Exp/Cntr=0.3,0.1

Type RM Length L Ch R = 1 ,2094.6  ,343.1,327.9,313.2
XS GIS Cut Line= 3
     1997925.649      306785.293     1997903.147      306578.038
     1997748.002      306369.598
#Sta/Elev= 30
       0 1890.24    19.8 1884.87    29.8 1882.07    59.6  1873.5    89.4 1864.86
    99.3  1861.9   109.2 1858.73   129.1 1851.72   148.9 1844.42   168.8 1836.95
   188.6 1829.29   218.5 1817.98   228.5  1814.7   232.71814.317   238.5 1813.79
   247.71815.667   248.4 1815.81   258.4 1820.15   268.4 1825.17   288.4 1834.26
   308.4  1843.5   318.4 1848.25   328.4 1852.82   338.4 1857.31   348.4  1861.5
   358.4 1865.34   368.4 1868.89   398.4 1878.39   418.4 1885.21   468.3 1903.64
#Mann= 3 , 0 , 0
       0      .1       0   232.7    .045       0   247.7      .1       0
Bank Sta=232.7,247.7
XS Rating Curve= 0 ,0
Exp/Cntr=0.3,0.1

Type RM Length L Ch R = 1 ,1766.5  ,363.3,373.6,383.6
XS GIS Cut Line= 4
      1998106.85      306415.786     1998049.692       306286.92
     1997964.869      306268.198     1997591.672      306177.738
#Sta/Elev= 30
       0 1833.29    18.8  1831.4    75.2  1823.7   103.4 1819.59   122.2 1815.88
   131.6 1813.38     141 1809.78   160.3 1798.83   169.9 1794.46   179.6 1790.94
   198.9 1785.19   220.31780.409   227.8 1779.51   235.31780.595   237.7 1780.94
   247.5 1787.39   267.2 1806.36   286.9 1821.77   326.3 1851.32   365.7 1879.49
   405.1 1905.29   414.9 1912.71   454.3 1945.52   464.2 1953.34     474 1960.27
   483.8 1965.54   513.4 1978.37   542.9  1992.5   572.5 2008.17   611.8  2029.9
#Mann= 3 , 0 , 0
       0      .1       0   220.3    .045       0   235.3      .1       0
Bank Sta=220.3,235.3
XS Rating Curve= 0 ,0
Exp/Cntr=0.3,0.1

Type RM Length L Ch R = 1 ,1392.7  ,304.2,296.7,289.2
XS GIS Cut Line= 3
     1998556.574      306309.206     1998071.321      305885.212
     1997822.614      305837.839
#Sta/Elev= 30
       0 1941.31    39.6 1925.35    79.3 1910.51     109 1900.43   168.5 1881.56
   188.4 1874.82   208.2  1866.7   257.8 1843.72   287.5 1830.52   307.3 1822.33
   337.1 1811.16   376.7 1797.77   426.3 1783.37   475.9 1767.49   505.6 1757.69
   535.3 1746.86   545.3 1746.14   547.41746.438   555.2 1747.53   562.41749.464
   584.9 1755.45   663.9 1774.18   673.6 1777.08   683.3 1781.06   693.1 1787.05
   751.5 1829.27   780.7 1851.53   819.7 1879.32   858.6  1906.1   897.6 1932.31
#Mann= 3 , 0 , 0
       0      .1       0   547.4    .045       0   562.4      .1       0
Bank Sta=547.4,562.4
XS Rating Curve= 0 ,0
Exp/Cntr=0.3,0.1

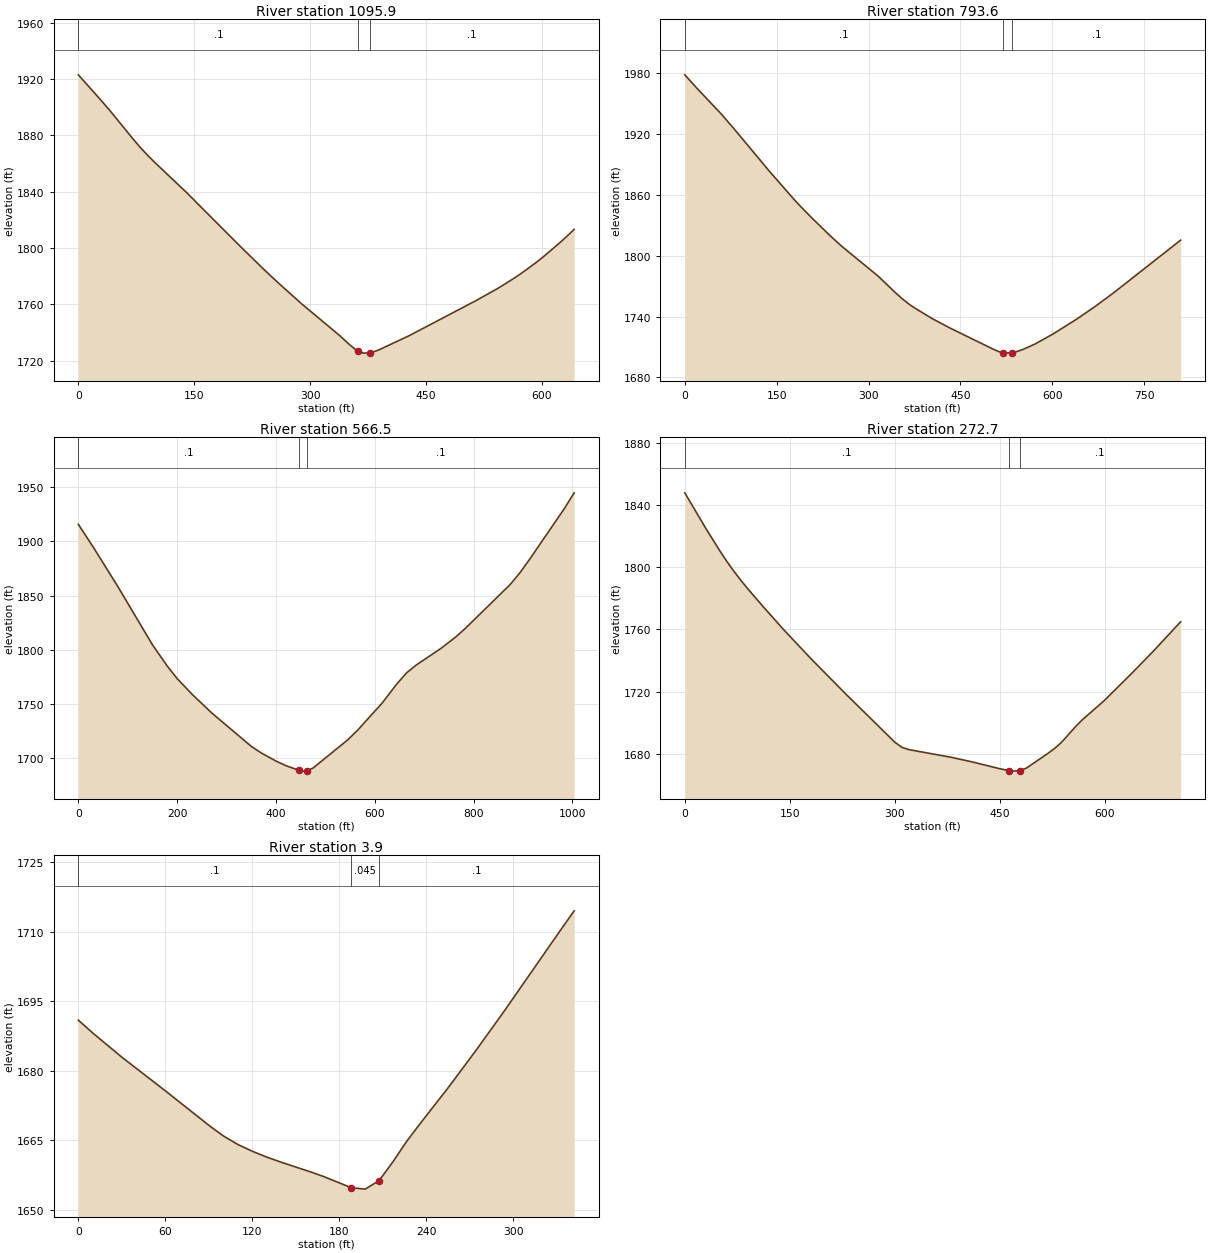
Type RM Length L Ch R = 1 ,1095.9  ,304.1,302.3,300.5
XS GIS Cut Line= 3
     1998635.648      305825.009     1998261.271      305687.988
     1998018.224      305678.153
#Sta/Elev= 30
       0 1923.01    29.9 1904.63    39.9 1898.29    69.8 1878.18    79.7 1871.78
    89.7 1865.88    99.7 1860.44   139.5 1839.79   209.3 1801.41   239.2  1785.4
   259.1 1775.18     289 1760.49   338.9 1737.64   348.8 1732.59   358.8 1727.97
   362.51727.031   368.8 1725.44   377.51725.643   378.7 1725.67   388.7 1727.66
   427.8 1737.68   515.4 1762.89   544.6 1771.89   564.1 1778.58   573.8 1782.19
   593.3 1790.02     603 1794.28   622.4 1803.37   632.2 1808.23   641.9 1813.34
#Mann= 3 , 0 , 0
       0      .1       0   362.5    .045       0   377.5      .1       0
Bank Sta=362.5,377.5
XS Rating Curve= 0 ,0
Exp/Cntr=0.3,0.1

Type RM Length L Ch R = 1 ,793.6   ,230.6,227,220.6
XS GIS Cut Line= 3
     1998825.139      305543.931     1998282.899      305396.164
     1998035.594      305384.443
#Sta/Elev= 30
       0 1978.63    19.7 1965.45    59.2 1940.17    78.9 1926.46     138 1883.57
   177.5 1856.28   187.3 1849.84   207.1  1837.6   236.6 1820.25   256.4 1809.34
   315.5 1780.07   345.1 1762.92     355 1757.64   364.8  1752.9   374.7 1748.76
   404.3 1737.93   433.8  1728.5   502.8  1708.1   512.7 1705.43     5201704.343
   522.6 1703.96     5351704.491   542.3 1705.52   552.2 1707.58   571.9 1712.96
   601.6 1722.96   641.2 1738.02     671 1750.44   700.7 1763.72   809.6 1815.47
#Mann= 3 , 0 , 0
       0      .1       0     520    .045       0     535      .1       0
Bank Sta=520,535
XS Rating Curve= 0 ,0
Exp/Cntr=0.3,0.1

Type RM Length L Ch R = 1 ,566.5   ,289.4,293.7,300
XS GIS Cut Line= 4
     1998769.871      305329.174     1998354.576      305181.797
       1998340.2      305181.622     1997792.218       305201.93
#Sta/Elev= 30
       0 1915.73      30 1894.84    80.1 1858.19   150.2 1804.42   180.3 1784.73
   200.3  1773.2   230.4 1758.81   270.4 1741.46   350.5 1710.62   370.6  1704.6
   400.6 1697.08   420.6  1692.9   447.51688.523     455 1687.94   462.51688.325
     475 1690.78   544.8 1716.64   564.7 1725.48   614.6 1750.61   644.5 1768.37
   664.4 1778.71   684.4 1786.04   734.2 1801.33   764.1 1811.87   784.1 1820.08
   873.8 1860.13   893.7 1871.06   913.7 1883.71   983.5 1930.24  1003.4  1944.8
#Mann= 3 , 0 , 0
       0      .1       0   447.5    .045       0   462.5      .1       0
Bank Sta=447.5,462.5
XS Rating Curve= 0 ,0
Exp/Cntr=0.3,0.1

Type RM Length L Ch R = 1 ,272.7   ,265.5,268.8,272.9
XS GIS Cut Line= 4
     1998809.348      305079.678     1998397.008       304899.07
     1998360.886      304888.608     1998143.564      304852.881
#Sta/Elev= 30
       0 1847.88      30    1825      50 1810.55      60 1803.75      70  1797.5
      80  1791.6      90  1786.1     110 1775.61     140 1760.38   180.1 1741.15
   230.1  1718.3   300.1  1687.3   310.1 1684.08   320.1 1682.59   380.1 1677.69
   410.2 1674.72   450.2 1670.26   463.21669.095     469 1668.76   478.21669.093
   487.8 1670.71   517.8 1679.94   527.8 1683.26   537.8 1687.24   557.8 1697.34
   567.8  1701.9   597.9 1713.72   637.9 1731.56     668 1745.48     708 1764.87
#Mann= 3 , 0 , 0
       0      .1       0   463.2    .045       0   478.2      .1       0
Bank Sta=463.2,478.2
XS Rating Curve= 0 ,0
Exp/Cntr=0.3,0.1

Type RM Length L Ch R = 1 ,3.9     ,0,3.9,13.2
XS GIS Cut Line= 3
     1998661.943      304743.377     1998534.133      304685.677
     1998354.827      304592.611
#Sta/Elev= 23
       0  1690.9      10 1688.11      30 1682.91    60.1 1675.64    90.2 1668.19
   100.2  1665.9   110.2 1664.06   120.2  1662.6   130.2 1661.34   140.2 1660.23
   159.5 1658.25   169.1 1657.19   188.3 1654.77     198 1654.45   207.6 1656.29
   217.2 1660.37   226.8 1664.84   236.4 1668.78   255.7  1676.5   274.9 1684.56
   294.2 1692.96   332.6 1710.22   342.2 1714.47
#Mann= 3 , 0 , 0
       0      .1       0   188.3    .045       0   207.6      .1       0
Bank Sta=188.3,207.6
XS Rating Curve= 0 ,0
Exp/Cntr=0.3,0.1

Chan Stop Cuts=-1
Use User Specified Reach Order=0
Composite Channel Slope=5